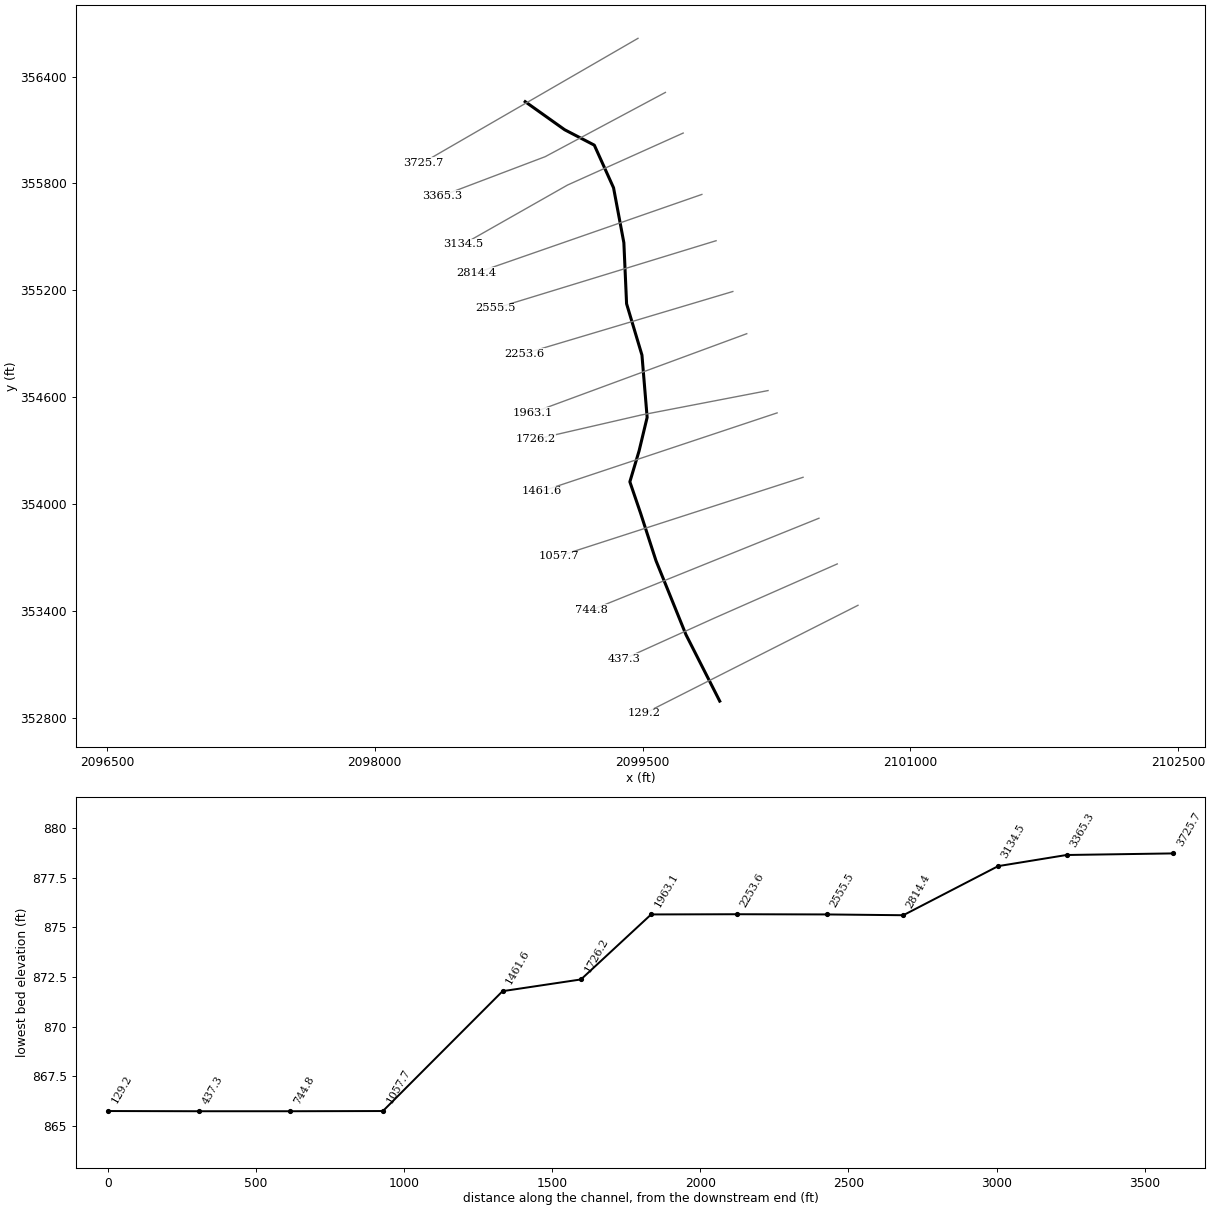
--- NBPOTRVR2.prj (project) ---

Proj Title=NBPOTRVR2
Current Plan=p01
Default Exp/Contr=0,0
English Units
Geom File=g01
Flow File=f01
Plan File=p01
BEGIN DESCRIPTION:
END DESCRIPTION:
DSS Export Rating Curves= 0
DSS Export Rating Curve Sorted= 0
DSS Export Volume Flow Curves= 0
DXF OffsetX= 0
DXF OffsetY= 0
DXF ScaleX= 0
DXF ScaleY= 0

--- NBPOTRVR2.p01 (plan) ---

Plan Title=Floodplain
Program Version=4.00
Geom File=g01
Flow File=f01
K Sum by GR=0
Std Step Tol=0.01
Critical Tol=0.01
Num of Std Step Trials=20
Max Error Tol=0.3
Flow Tol Ratio=0.001
Split Flow NTrial=30
Split Flow Tol=0.02
Split Flow Ratio=0.02
Log Output Level=0
Friction Slope Method=1
Unsteady Friction Slope Method=2
Unsteady Bridges Friction Slope Method=1
Global Log Level=0
CheckData=False
Run HTab=0
Run UNet=0
Run PostProcess=0
UNET Theta=0
UNET Theta Warmup=0
UNET ZTol=0
UNET ZSATol=0
UNET MxIter=0
UNET MaxInSteps=0
UNET DtIC=0
UNET DtMin=0
UNET MaxCRTS=0
UNET WFStab=0
UNET SFStab=0
UNET WFX=0
UNET SFX=0
UNET DSS MLevel=0
UNET DZMax Abort=0
UNET Convert EG Bridges=0
UNET Use Existing IB Tables=0
UNET Froude Limit=0
UNET Froude Power=0
Write IC File=0
Echo Input=False
Echo Output=False
Write Detailed=0

--- NBPOTRVR2.f01 (steady flow) ---

Flow Title=NFF Regression Equation
Program Version=4.00
Number of Profiles= 1
Profile Names=P100yr
River Rch & RM=NBPOTRVR2,Main            ,3725.7
   53519
River Rch & RM=NBPOTRVR2,Main            ,129.2
   53648
Boundary for River Rch & Prof#=NBPOTRVR2,Main            , 1
Up Type= 0
Dn Type= 1
Dn Known WS=894
DSS Import GetInterval= 0
DSS Import GetPeak= 0
DSS Import FillOption= 0

--- NBPOTRVR2.g01 (geometry) ---

Geom Title=USGS 10m DEM
Program Version=4.00

River Reach=NBPOTRVR2       ,Main
Reach XY= 15
     2098842.595      356258.952     2099063.539      356101.577
     2099229.749      356014.995     2099337.503      355775.707
     2099395.264      355467.407     2099410.519      355124.877
     2099496.523      354837.057     2099525.636      354487.272
     2099480.608      354299.463     2099428.833      354125.663
     2099446.324      354074.462     2099488.753      353950.058
     2099575.128      353683.183     2099742.865      353268.232
     2099932.257      352894.914

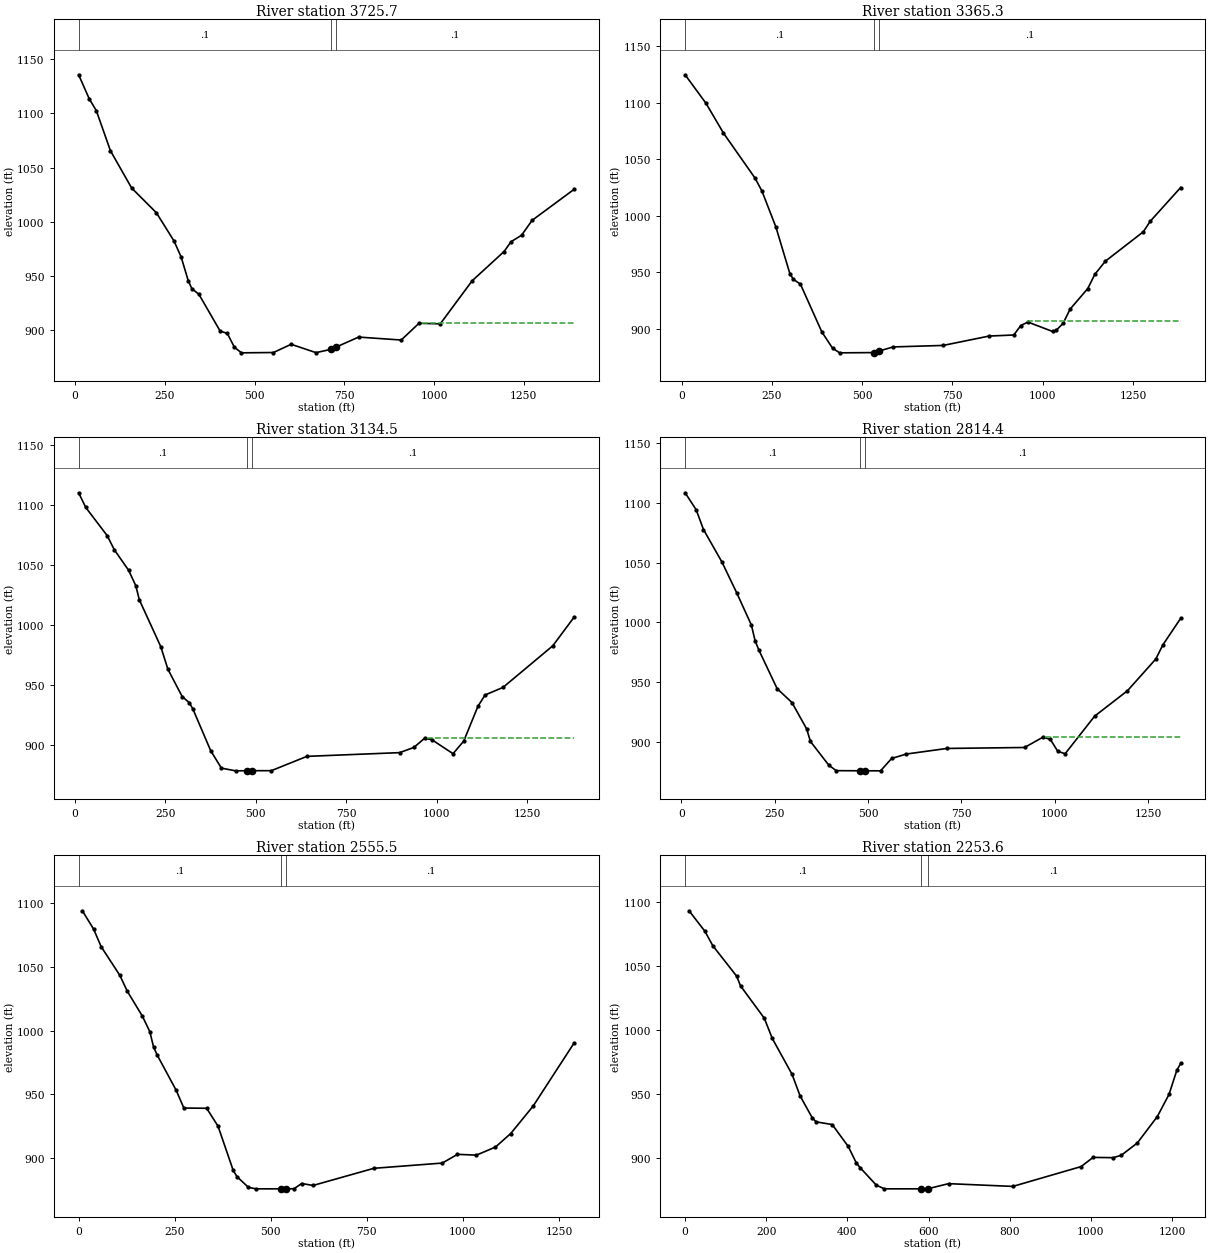
Type RM Length L Ch R = 1 ,3725.7  ,362.4,360.4,358.4
XS GIS Cut Line= 5
     2099474.398       356614.43     2099244.451      356481.224
      2098850.74      356253.151      2098457.03      356025.078
     2098271.108      355917.375
#Sta/Elev= 30
     9.8 1135.73    39.4 1113.48    59.1 1102.57    98.4 1065.55   157.5 1031.07
   226.4 1008.23   275.6  982.11   295.4  967.35   315.2  945.41   325.1  938.17
   344.9  932.82   404.2   898.8     424  896.72   443.8  883.92   463.6  878.72
   552.6  879.02     602  886.61   671.3  878.91   713.2  881.96   728.2  884.18
     790  893.29   908.7  890.56   958.1  906.02  1017.5  905.52  1106.5  945.37
  1195.3  972.37  1214.8  981.46  1244.1  987.43  1273.4 1001.19  1390.6  1029.9
#Mann= 3 , 0 , 0
     9.8      .1       0   713.2    .045       0   728.2      .1       0
#XS Ineff= 2 , 0
                          967.23          906.35
Permanent Ineff=
       F       F
Bank Sta=713.2,728.2
XS Rating Curve= 0 ,0
Exp/Cntr=0.3,0.1

Type RM Length L Ch R = 1 ,3365.3  ,231,230.8,230.5
XS GIS Cut Line= 5
     2099627.919      356310.959     2099355.157      356164.858
     2098954.605      355950.309     2098525.886      355787.522
     2098376.722      355730.884
#Sta/Elev= 30
     9.7 1124.54    67.7 1099.27     116 1072.95   203.1 1033.29   222.4 1021.81
   261.1  989.96   299.8  948.72   309.4  943.72   329.2   939.3   388.5  897.05
   418.1  882.74   437.8  878.64     533  878.86     548  880.36     586  883.87
   724.3  885.19   851.6  893.48   919.9  894.42   939.4  902.76     959  905.85
  1027.3  897.55    1037  898.47  1056.5   904.7    1076  917.35  1124.8  935.47
  1144.3  948.01  1173.6   959.7  1278.7  985.69  1297.5  994.87    1382 1024.82
#Mann= 3 , 0 , 0
     9.7      .1       0     533    .045       0     548      .1       0
#XS Ineff= 2 , 0
                          958.55          906.73
Permanent Ineff=
       F       F
Bank Sta=533,548
XS Rating Curve= 0 ,0
Exp/Cntr=0.3,0.1

Type RM Length L Ch R = 1 ,3134.5  ,322.2,320.2,318.2
XS GIS Cut Line= 5
      2099727.57      356082.862      2099493.34      355977.387
     2099079.807       355791.17     2098677.035      355562.111
     2098497.189      355459.832
#Sta/Elev= 30
     9.9 1110.25    29.6    1098    88.9 1074.47   108.7 1062.62   148.2 1045.54
     168 1032.66   177.8 1020.89   237.1  981.79   256.9  962.87   296.3  940.15
     316  935.01   325.9  929.77   375.2  894.92   404.8  880.35   444.2  878.08
   474.3  878.18   489.3  878.21   542.8   878.2   641.4  890.17   897.7  893.28
   937.2  897.59   966.7  905.21   986.4  904.19  1045.6   892.4  1075.2  902.91
  1114.6  932.03  1134.3  941.44  1183.6  947.69  1321.5  982.46  1380.7 1006.48
#Mann= 3 , 0 , 0
     9.9      .1       0   474.3    .045       0   489.3      .1       0
#XS Ineff= 2 , 0
                          977.15          905.58
Permanent Ineff=
       F       F
Bank Sta=474.3,489.3
XS Rating Curve= 0 ,0
Exp/Cntr=0.3,0.1

Type RM Length L Ch R = 1 ,2814.4  ,259.6,258.8,258.1
XS GIS Cut Line= 5
     2099832.199      355738.456     2099589.853      355653.973
     2099160.211      355504.198     2098730.569      355354.423
     2098569.061      355298.121
#Sta/Elev= 30
     9.9 1108.42    39.5 1094.27    59.2 1077.63   108.6 1050.45   148.1 1024.73
   187.6  997.61   197.4   984.6   207.3  976.94   256.6  944.36   296.2  932.82
   335.8  910.61   345.7  900.23   395.1   880.3   414.9  875.76   477.3  875.66
   492.3  875.66   533.6  875.61   563.3  885.96   602.8  889.69   711.6  894.36
   919.4  895.16   968.8   903.8   988.6  901.93  1008.4  891.97  1028.2  889.93
  1107.3   921.4  1195.2  942.67  1271.2  969.25  1290.2  981.15  1337.7 1003.23
#Mann= 3 , 0 , 0
     9.9      .1       0   477.3    .045       0   492.3      .1       0
#XS Ineff= 2 , 0
                          977.15          904.06
Permanent Ineff=
       F       F
Bank Sta=477.3,492.3
XS Rating Curve= 0 ,0
Exp/Cntr=0.3,0.1

Type RM Length L Ch R = 1 ,2555.5  ,302.2,301.9,301.6
XS GIS Cut Line= 5
     2099911.788      355478.647     2099706.755      355415.729
     2099271.775      355282.247     2098836.795      355148.766
     2098678.823      355100.289
#Sta/Elev= 30
     9.7 1094.05      39 1079.67    58.5 1065.94   107.2 1043.34   126.7 1030.83
   165.7 1011.41   185.2  999.15     195  987.12   204.7  980.59     254  952.98
   273.8  939.12   333.2  938.93   362.8  924.87   402.4  890.06   412.3  885.15
     442  876.81   461.8  875.65     526  875.66     541  875.66   560.7  875.73
   580.4  879.84   610.1  878.31   768.4  891.78   946.4  895.89     986  902.74
  1035.4  902.14  1084.9  908.47  1124.5  919.07  1182.8   940.6  1289.7  990.29
#Mann= 3 , 0 , 0
       0      .1       0     526    .045       0     541      .1       0
Bank Sta=526,541
XS Rating Curve= 0 ,0
Exp/Cntr=0.3,0.1

Type RM Length L Ch R = 1 ,2253.6  ,288.9,290.5,292.1
XS GIS Cut Line= 5
     2100005.618      355193.682     2099753.083      355118.222
      2099317.13      354987.954     2098881.176      354857.686
     2098835.679      354844.091
#Sta/Elev= 30
     9.8 1092.89    48.8 1076.88    68.3 1065.58   126.9 1041.87   136.7 1034.17
   195.2 1008.94   214.8  993.17   263.6   965.1   283.4  948.24     313  931.32
   322.9  927.99   362.5  925.89     402  908.79   421.8  895.95   431.7  892.06
   471.3  878.52   491.1  875.66   582.4  875.66   597.4  875.66   649.3  879.71
   807.6  877.56   975.7  893.04  1005.4  900.22  1054.9  900.01  1074.7  901.85
  1114.2  911.43  1163.7  932.16  1192.6  949.52  1211.6  968.22  1221.1   973.6
#Mann= 3 , 0 , 0
       0      .1       0   582.4    .045       0   597.4      .1       0
Bank Sta=582.4,597.4
XS Rating Curve= 0 ,0
Exp/Cntr=0.3,0.1

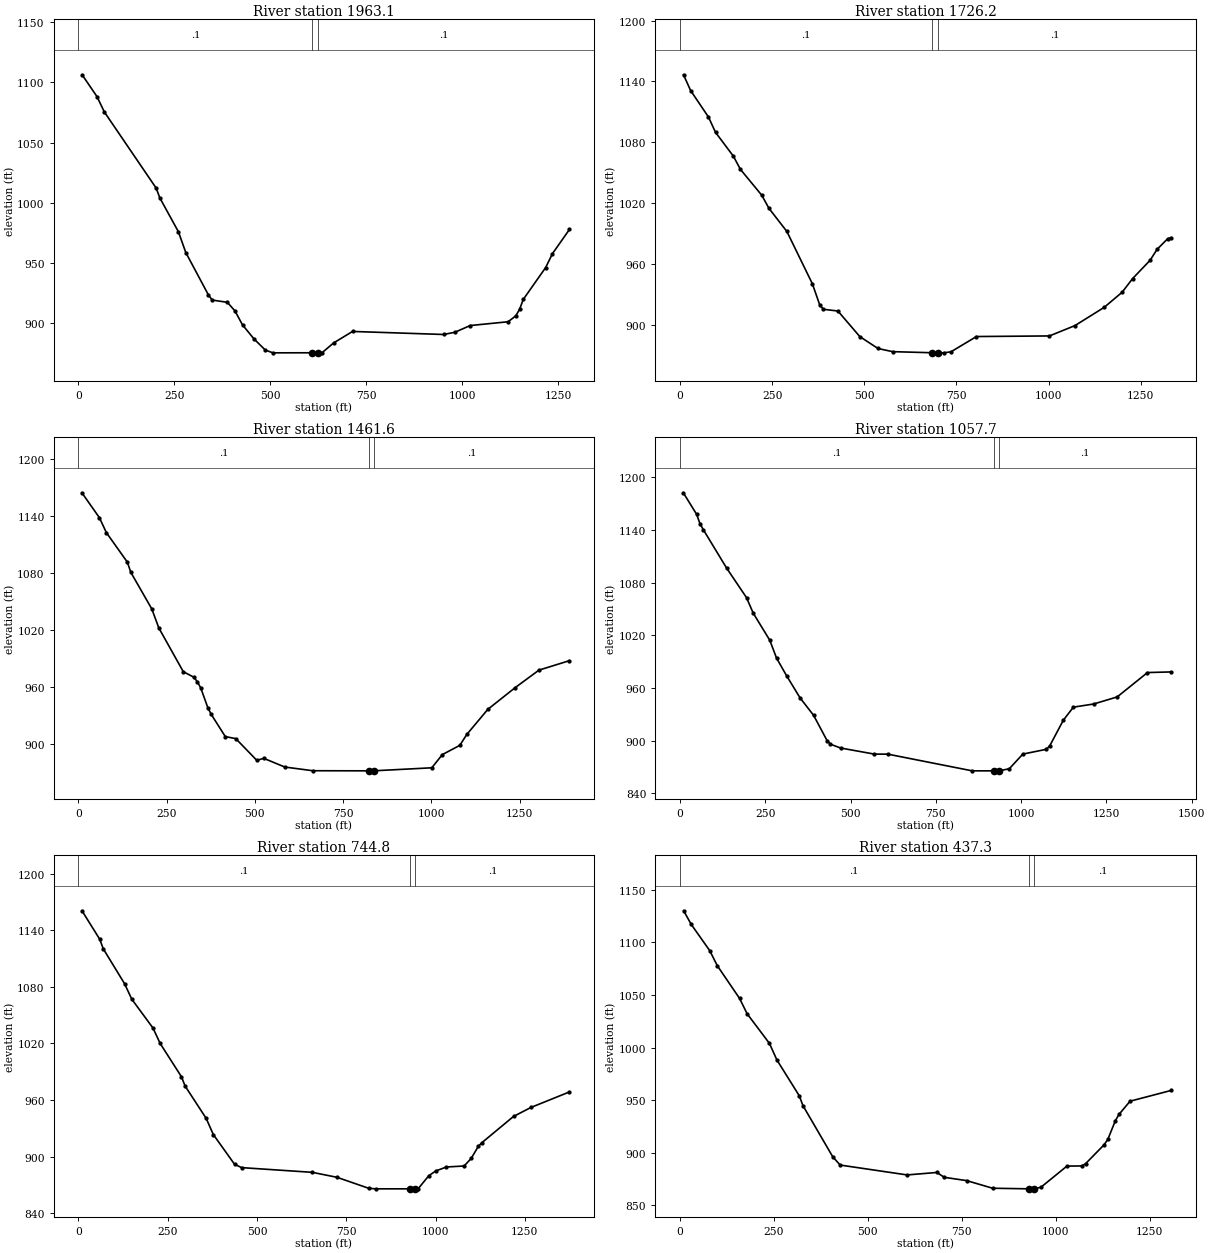
Type RM Length L Ch R = 1 ,1963.1  ,240.8,236.9,233.1
XS GIS Cut Line= 5
     2100083.594      354956.867     2099802.973      354853.163
     2099376.183      354695.443     2098949.394      354537.722
     2098882.819      354513.119
#Sta/Elev= 30
     9.7 1106.24    48.3  1088.2    67.6 1075.41   202.7 1012.24   212.3 1004.09
   260.6   976.1   279.9  958.84   338.7  923.79   348.6  919.42   388.2  917.55
     408  910.47   427.8  898.82   457.4   887.3   487.1  877.96   506.9  875.65
     610   875.7     625  875.67   635.5  875.85   665.1  883.83   714.6  893.39
     952  890.87   981.7  892.75  1021.2  898.29  1120.1  901.43  1139.9  906.27
  1149.8  911.61  1159.7     920    1218   946.4  1235.8  957.96  1280.1  978.03
#Mann= 3 , 0 , 0
       0      .1       0     610    .045       0     625      .1       0
Bank Sta=610,625
XS Rating Curve= 0 ,0
Exp/Cntr=0.3,0.1

Type RM Length L Ch R = 1 ,1726.2  ,259.7,264.6,269.5
XS GIS Cut Line= 5
     2100202.825        354637.7     2099937.606       354586.51
     2099490.913      354500.293     2099047.197      354397.986
     2098899.457      354363.922
#Sta/Elev= 30
     9.6 1146.61    28.9 1131.05    77.2    1105    96.5 1089.78   144.7  1066.4
     164 1053.32   221.9 1027.78   241.2 1014.97   289.9   992.1   359.1  940.51
   378.9  919.83   388.8  915.34   428.4  913.62   487.7  888.44   537.1  876.66
   576.7  873.55   683.8  872.47   698.8  872.41   715.2  872.38     735  873.38
   804.2  888.46  1002.2  889.05  1071.5  899.27  1150.7  917.25  1199.4  932.19
  1227.8  945.66  1275.2  963.67  1294.1  974.47  1322.5  984.82    1332  985.97
#Mann= 3 , 0 , 0
       0      .1       0   683.8    .045       0   698.8      .1       0
Bank Sta=683.8,698.8
XS Rating Curve= 0 ,0
Exp/Cntr=0.3,0.1

Type RM Length L Ch R = 1 ,1461.6  ,405.7,403.9,402.1
XS GIS Cut Line= 4
     2100253.621      354512.402      2100009.36      354430.925
     2099134.262      354139.023     2098933.508      354072.059
#Sta/Elev= 30
     9.9 1164.53    59.4 1138.37    79.2 1122.62   138.6 1091.56   148.6 1080.71
     208 1042.22   227.8  1022.3   297.2  976.17   326.9  970.42   336.8  965.74
   346.8  958.97   366.6  938.39   376.5  931.16   416.2  907.87     446  905.69
   505.5  882.85   525.3  884.95   584.8   875.8   664.2  871.91   822.9  871.79
     823  871.79     838  871.84  1001.4     875  1031.2  888.87  1080.8  898.62
  1100.6  910.12  1160.2  936.54  1237.7   959.4    1305  977.81  1391.6  987.81
#Mann= 3 , 0 , 0
       0      .1       0     823    .045       0     838      .1       0
Bank Sta=823,838
XS Rating Curve= 0 ,0
Exp/Cntr=0.3,0.1

Type RM Length L Ch R = 1 ,1057.7  ,311.3,312.9,314.5
XS GIS Cut Line= 5
     2100399.042      354151.093     2100120.471      354060.932
      2099687.58      353920.826     2099254.688       353780.72
     2099029.413      353707.809
#Sta/Elev= 30
     9.8 1182.55    48.8 1158.02    58.6 1147.39    68.3  1140.6   136.6 1096.85
   195.2 1063.01   214.7 1045.44   263.5 1014.41     283  994.27   312.6  974.05
   352.1  948.86   391.7  929.03   431.3  900.14   441.2  896.11   470.8  891.77
   569.8  884.83   609.3  884.77   856.6  865.76   920.5  865.76   935.5  865.76
   965.4  868.15    1005  884.84  1074.2  890.31  1084.1  894.33  1123.7  923.39
  1153.3  938.33  1212.7   941.9  1281.7  949.98  1370.5  977.73  1439.6  978.46
#Mann= 3 , 0 , 0
       0      .1       0   920.5    .045       0   935.5      .1       0
Bank Sta=920.5,935.5
XS Rating Curve= 0 ,0
Exp/Cntr=0.3,0.1

Type RM Length L Ch R = 1 ,744.8   ,306.6,307.5,308.4
XS GIS Cut Line= 5
     2100488.017      353921.242     2100211.184      353809.336
     2099789.346      353638.815     2099367.507      353468.294
     2099213.116      353405.883
#Sta/Elev= 30
      10 1160.53    59.7 1130.36    69.7 1120.14   129.4 1083.13   149.3 1066.88
     209 1036.13   228.9 1019.87   288.6  984.56   298.6  974.84   357.9  940.36
   377.7  923.33   437.1  891.86   456.9  888.25   654.7  883.25   723.9     878
   812.9  866.33   832.7  865.75   928.1  865.76   943.1  865.77   951.4  865.88
   981.1  879.68  1000.9  884.77  1030.6  888.92    1080  889.96  1099.8  897.97
  1119.6  910.68  1129.5   914.6  1218.4  942.51  1267.4  952.07  1375.1   968.5
#Mann= 3 , 0 , 0
       0      .1       0   928.1    .045       0   943.1      .1       0
Bank Sta=928.1,943.1
XS Rating Curve= 0 ,0
Exp/Cntr=0.3,0.1

Type RM Length L Ch R = 1 ,437.3   ,307.1,308.1,309.1
XS GIS Cut Line= 5
     2100590.526       353664.85     2100318.257      353544.609
     2099901.777       353360.68     2099487.421      353172.937
      2099397.17      353132.046
#Sta/Elev= 30
     9.9 1130.01    29.8 1117.14    79.4 1092.01    99.2 1077.89   158.7 1046.67
   178.6  1032.2   238.1 1003.97     258  988.19   317.4  954.24   327.3  944.82
   406.5  896.26   426.3  888.35   604.5  878.97   683.6  881.31   703.4  876.69
   762.8  873.58     832  866.32   927.6  865.76   940.8  865.75   942.6  865.78
   960.6  867.25  1029.8  887.38  1069.4  887.49  1079.3  889.61  1128.7  907.63
  1138.6  912.74  1158.4  930.26  1168.3  936.49  1197.9  949.05  1306.9  959.24
#Mann= 3 , 0 , 0
       0      .1       0   927.6    .045       0   942.6      .1       0
Bank Sta=927.6,942.6
XS Rating Curve= 0 ,0
Exp/Cntr=0.3,0.1

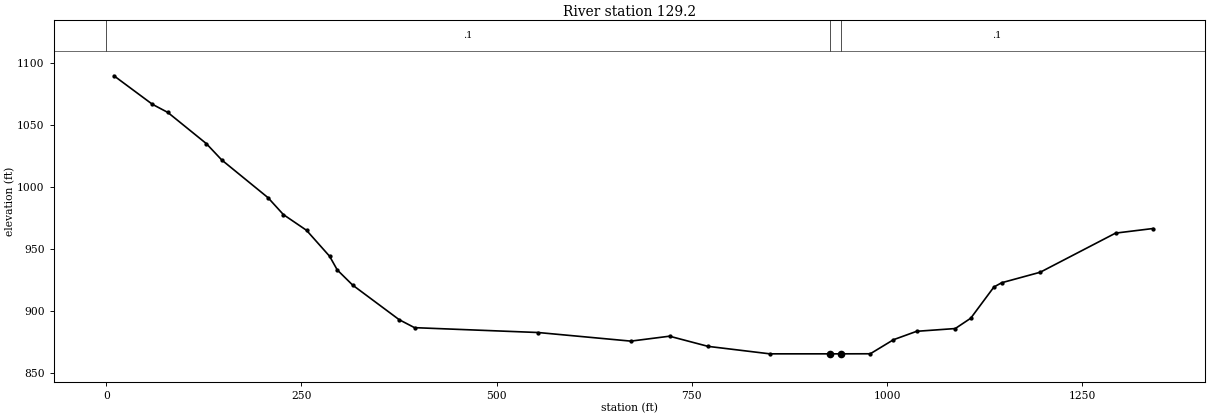
Type RM Length L Ch R = 1 ,129.2   ,129.2,129.2,129.2
XS GIS Cut Line= 5
     2100706.635      353432.632     2100442.722      353298.744
     2100036.953      353092.888     2099631.184      352887.033
     2099511.157      352826.141
#Sta/Elev= 30
     9.9 1089.93    59.2 1066.92    78.9 1060.38   128.2 1035.26     148 1022.03
   207.2  991.66   226.9  978.02   256.5  965.36   286.1   944.4   295.9  933.38
   315.7  921.12   375.1  893.32   394.8  886.87   553.1  882.95   671.8  876.01
   721.3  879.98   770.7  871.78   849.8  865.76   926.4  865.76   941.4  865.76
   978.4  865.81  1008.1  877.15  1037.8  883.93  1087.2  886.15    1107  894.46
  1136.7  919.64  1146.6  923.07    1196  931.55  1292.5  963.09  1340.5   966.8
#Mann= 3 , 0 , 0
       0      .1       0   926.4    .045       0   941.4      .1       0
Bank Sta=926.4,941.4
XS Rating Curve= 0 ,0
Exp/Cntr=0.3,0.1

Chan Stop Cuts=-1
Use User Specified Reach Order=0